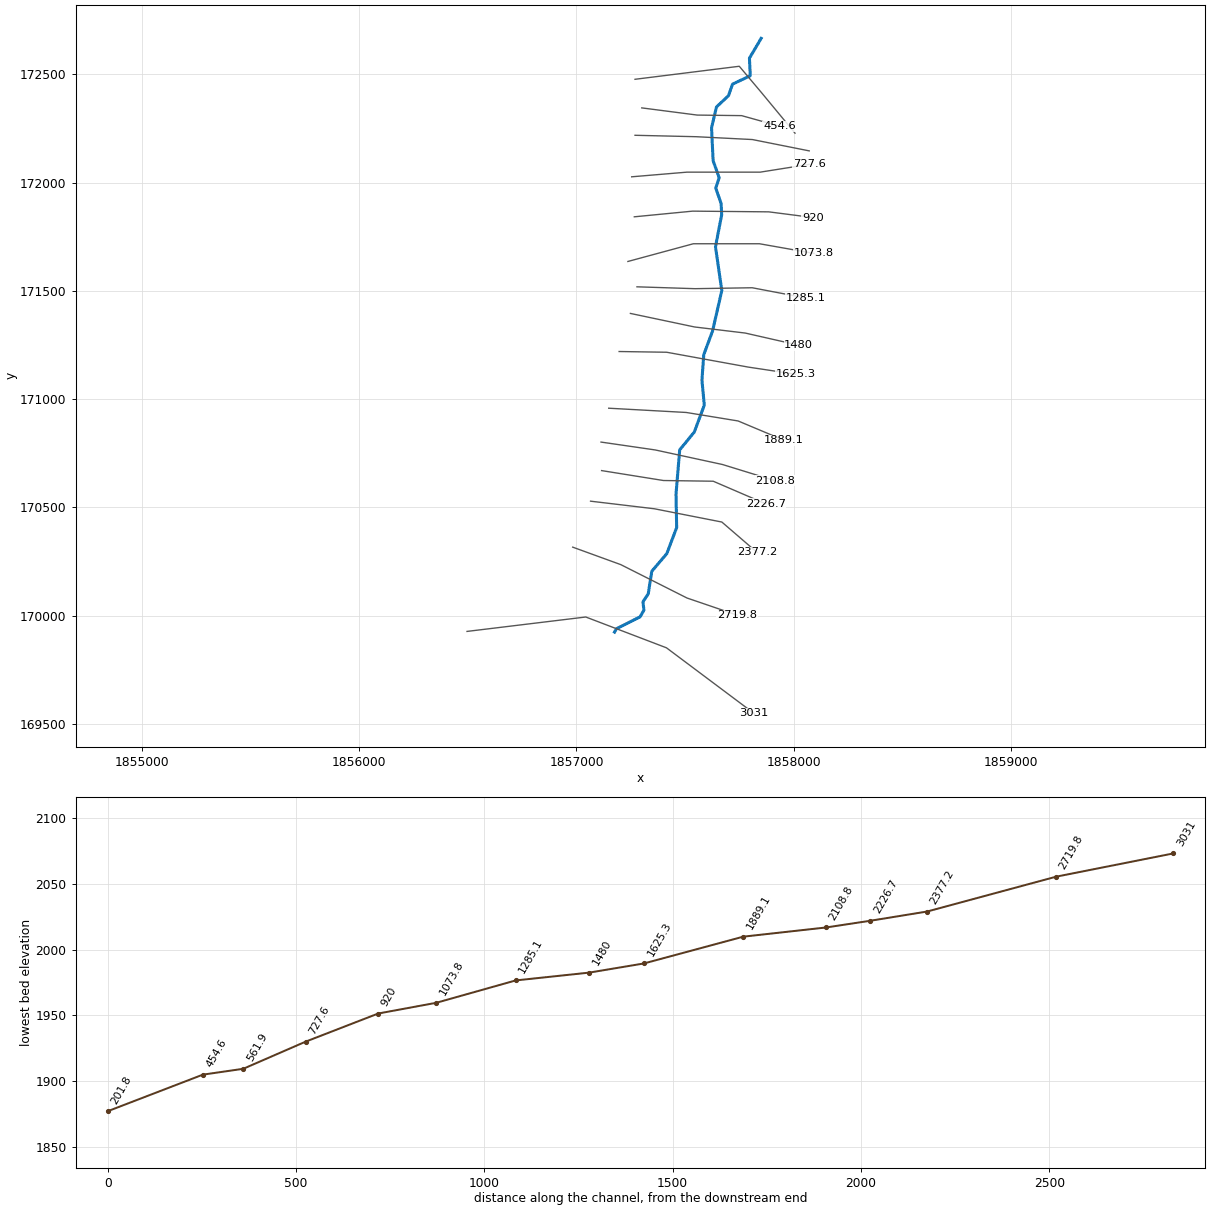
--- LtlPinclCr.prj (project) ---

Proj Title=LtlPinclCr
Current Plan=p01
Geom File=g01
Flow File=f01
Plan File=p01
DSS Export Rating Curves=0
DSS Export Rating Curve Sorted=0
DSS Export Volume Flow Curves=0
DXF OffsetX=0
DXF OffsetY=0
DXF ScaleX=0
DXF ScaleY=0

--- LtlPinclCr.p01 (plan) ---

Plan Title=Floodplain
Program Version=4.00
Geom File=g01
Flow File=f01
K Sum by GR=0
Std Step Tol=0.01
Critical Tol=0.01
Num of Std Step Trials=20
Max Error Tol=0.3
Flow Tol Ratio=0.001
Split Flow NTrial=30
Split Flow Tol=0.02
Split Flow Ratio=0.02
Log Output Level=0
Friction Slope Method=1
Unsteady Friction Slope Method=2
Unsteady Bridges Friction Slope Method=1
Global Log Level=0
CheckData=False
Run HTab=0
Run UNet=0
Run PostProcess=0
UNET Theta=0
UNET Theta Warmup=0
UNET ZTol=0
UNET ZSATol=0
UNET MxIter=0
UNET MaxInSteps=0
UNET DtIC=0
UNET DtMin=0
UNET MaxCRTS=0
UNET WFStab=0
UNET SFStab=0
UNET WFX=0
UNET SFX=0
UNET DSS MLevel=0
UNET DZMax Abort=0
UNET Convert EG Bridges=0
UNET Use Existing IB Tables=0
UNET Froude Limit=0
UNET Froude Power=0
Write IC File=0
Echo Input=False
Echo Output=False
Write Detailed=0

--- LtlPinclCr.f01 (steady flow) ---

Flow Title=NFF Regression Equation
Program Version=4.00
Number of Profiles=1
Profile Names=P100yr
River Rch & RM=LtlPinclCr,Main      ,3031
505.1764
River Rch & RM=LtlPinclCr,Main      ,2719.8
576.8806
River Rch & RM=LtlPinclCr,Main      ,201.8
617.6109
Boundary for River Rch & Prof#=LtlPinclCr,Main      ,1
Up Type=0
Dn Type=3
Dn Slope=0.093611

--- LtlPinclCr.g01 (geometry) ---

Geom Title=USGS 10m DEM
Program Version=4.00

River Reach=LtlPinclCr     ,Main
Reach XY= 30
     1857175.355      169923.325     1857184.447      169939.084
     1857293.548      169994.241     1857310.519      170025.152
     1857306.276      170063.337     1857330.521      170100.311
     1857346.886      170204.562     1857415.983      170285.781
     1857461.442      170406.398     1857458.411      170560.958
     1857475.382      170765.218     1857542.661      170847.650
     1857588.726      170971.904     1857577.816      171087.671
     1857586.301      171205.257     1857626.911      171314.964
     1857669.339      171501.042     1857640.245      171703.484
     1857668.733      171851.376     1857666.308      171902.895
     1857641.458      171975.023     1857657.217      172022.300
     1857629.335      172101.095     1857622.062      172253.836
     1857644.979      172349.763     1857700.150      172401.627
     1857718.737      172454.965     1857800.361      172493.756
     1857796.664      172575.122     1857850.630      172666.613

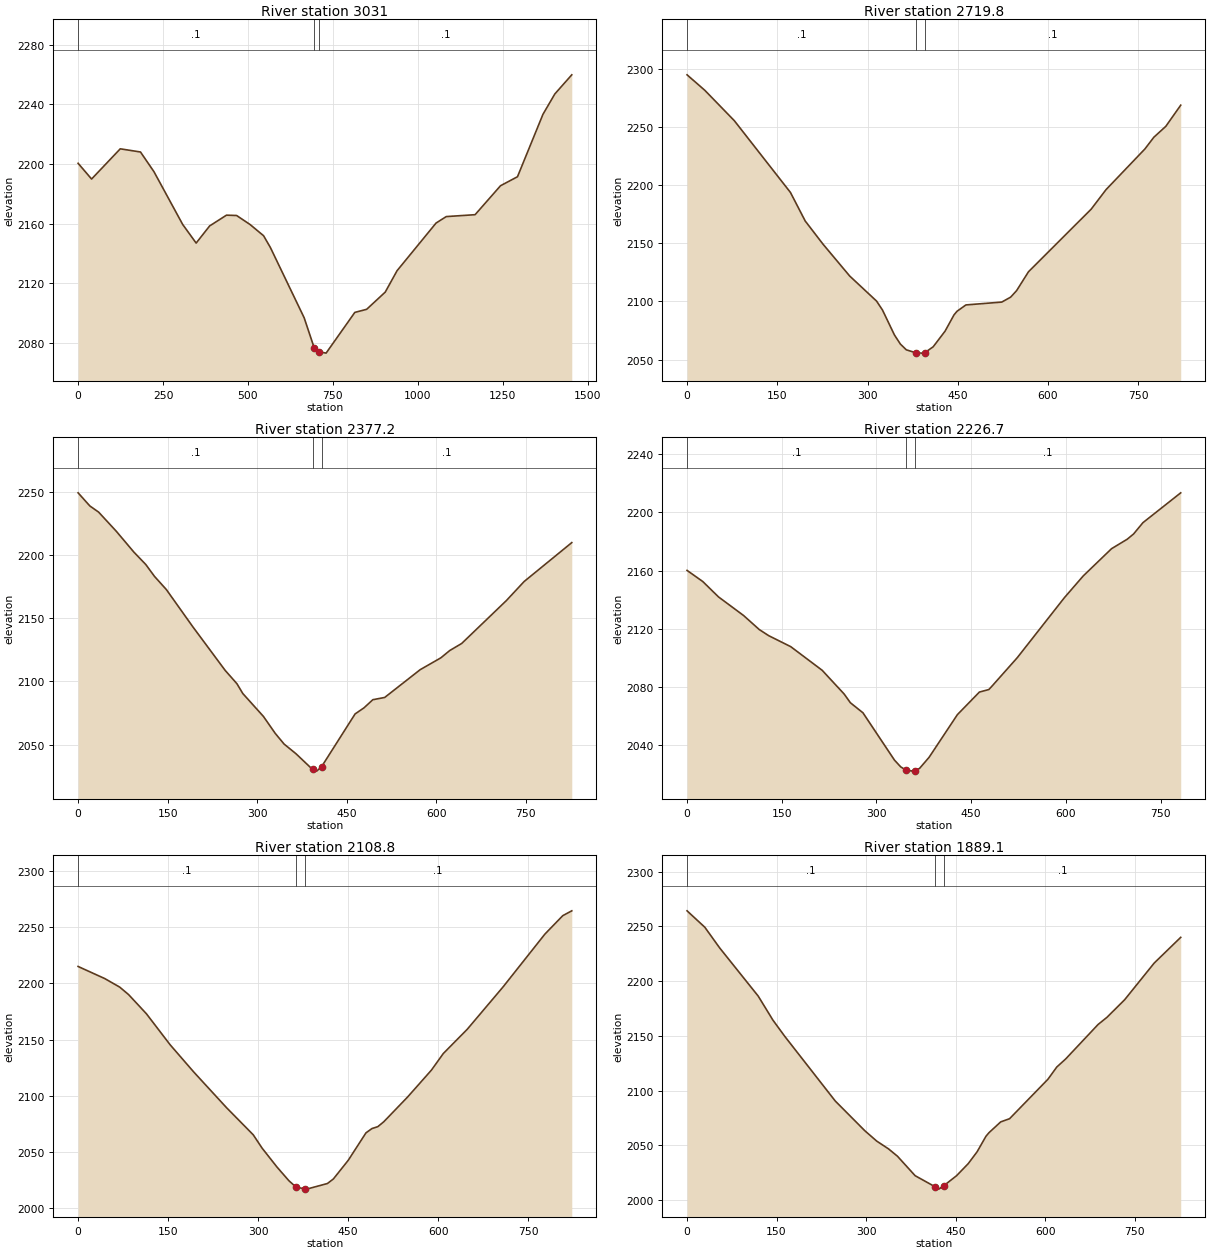
Type RM Length L Ch R = 1 ,3031,315.9,311.2,302.6
XS GIS Cut Line= 4
     1856495.950      169926.547     1857042.893      169993.162
     1857414.440      169850.813     1857817.731      169547.893
#Sta/Elev= 30
       0 2200.52    39.7 2189.95   124.1 2210.21   183.7 2208.08   223.4 2194.84
   307.8 2159.53   347.5 2147.00   387.2 2158.50   436.8 2165.72   466.6 2165.50
   506.3 2159.44   546.0 2151.93   565.9 2144.10   665.4 2096.94   695.1 2076.66
   710.1 2074.07   710.1 2074.08   730.0 2073.21   814.6 2100.52   849.4 2102.59
   904.1 2114.12   938.9 2128.48  1053.7 2160.43  1083.7 2164.77  1168.6 2166.04
  1243.5 2185.46  1293.4 2191.49  1368.4 2233.36  1403.3 2246.99  1453.2 2259.83
#Mann= 3 , 0 , 0
       0     0.1       0   695.1   0.045       0   710.1     0.1       0
Bank Sta=   695.1,   710.1
Exp/Cntr=0.3,0.1

Type RM Length L Ch R = 1 ,2719.8,336.1,342.6,349.2
XS GIS Cut Line= 4
     1856982.701      170315.853     1857204.172      170235.079
     1857509.198      170080.813     1857739.231      170002.048
#Sta/Elev= 30
       0 2295.02    29.5 2281.72    78.6 2255.54   171.9 2193.78   196.4 2169.25
   225.9 2149.36   270.4 2121.86   315.0 2100.33   324.9 2092.60   344.7 2071.21
   354.6 2063.33   364.5 2058.36   379.9 2055.86   389.3 2055.51   394.9 2055.77
   409.1 2060.93   428.9 2074.40   443.8 2088.43   448.8 2091.53   463.6 2096.99
   523.1 2099.43   537.9 2103.67   547.8 2109.26   567.6 2125.53   671.8 2179.39
   696.6 2196.25   761.2 2231.25   776.0 2241.29   795.9 2250.68   820.7 2268.91
#Mann= 3 , 0 , 0
       0     0.1       0   379.9   0.045       0   394.9     0.1       0
Bank Sta=   379.9,   394.9
Exp/Cntr=0.3,0.1

Type RM Length L Ch R = 1 ,2377.2,146.3,150.5,154.7
XS GIS Cut Line= 4
     1857064.806      170528.273     1857358.438      170493.212
     1857669.600      170431.856     1857831.755      170291.614
#Sta/Elev= 30
       0 2249.33    19.7 2238.94    34.5 2234.01    64.1 2218.85    93.6 2202.33
   113.4 2192.60   128.1 2183.13   147.9 2172.75   192.2 2143.31   246.4 2108.79
   266.2 2098.19   276.0 2090.45   310.6 2072.29   330.4 2058.86   345.3 2050.39
   365.1 2042.78     393 2030.30   399.8 2029.00     408 2032.49   464.2 2074.28
   479.1 2079.10   493.9 2085.54   513.8 2087.32   573.2 2109.30   607.9 2118.69
   622.8 2124.47   642.8 2130.06   717.6 2163.97   747.5 2179.13   827.3 2209.91
#Mann= 3 , 0 , 0
       0     0.1       0     393   0.045       0     408     0.1       0
Bank Sta=     393,     408
Exp/Cntr=0.3,0.1

Type RM Length L Ch R = 1 ,2226.7,122.5,117.9,113.4
XS GIS Cut Line= 4
     1857115.708      170669.565     1857400.640      170623.714
     1857629.897      170620.439     1857872.253      170515.636
#Sta/Elev= 30
       0 2160.11    24.9 2152.45    49.8 2141.87    89.6 2129.04   114.4 2119.39
   129.4 2115.17   164.2 2107.64   214.0 2091.37   248.8 2075.05   258.7 2069.03
   278.6 2062.12   328.5 2029.59   338.4 2024.92   346.8 2022.68   358.4 2021.99
   361.8 2022.25   368.4 2023.95   383.3 2031.47   428.2 2060.87   463.0 2076.38
   478.0 2078.13   483.0 2080.48   522.9 2099.99   597.6 2141.31   627.5 2156.30
   672.3 2175.03   697.2 2181.57   707.2 2185.16   722.1 2192.97   781.9 2213.48
#Mann= 3 , 0 , 0
       0     0.1       0   346.8   0.045       0   361.8     0.1       0
Bank Sta=   346.8,   361.8
Exp/Cntr=0.3,0.1

Type RM Length L Ch R = 1 ,2108.8,218.9,219.6,220.4
XS GIS Cut Line= 4
     1857113.151      170801.288     1857362.821      170764.931
     1857672.179      170697.742     1857914.763      170622.753
#Sta/Elev= 30
       0 2215.03    44.5 2204.24    69.3 2196.68    84.1 2190.03   113.8 2172.98
   153.4 2145.34   192.9 2121.02   247.4 2089.36   291.9 2065.22   306.7 2053.34
   331.4 2036.59   351.2 2024.43   362.6 2018.96   377.6 2016.99   380.9 2016.87
   415.5 2021.86   425.4 2025.87   450.2 2042.50   479.8 2066.95   489.7 2070.76
   499.6 2072.49   509.5 2076.84   549.1 2098.81   588.8 2122.73   608.7 2137.56
   648.5 2159.08   708.3 2196.84   778.0 2243.83   807.8 2260.24   822.8 2264.55
#Mann= 3 , 0 , 0
       0     0.1       0   362.6   0.045       0   377.6     0.1       0
Bank Sta=   362.6,   377.6
Exp/Cntr=0.3,0.1

Type RM Length L Ch R = 1 ,1889.1,264.2,263.8,263.5
XS GIS Cut Line= 4
     1857148.458      170957.773     1857505.443      170938.123
     1857744.525      170898.822     1857954.130      170810.394
#Sta/Elev= 30
       0 2264.26    29.8 2249.24    54.6 2230.40   119.2 2186.35   144.0 2164.28
   163.9 2149.42   248.3 2090.47   297.9 2063.25   317.8 2053.80   337.7 2046.64
   352.6 2039.96   382.2 2022.17   415.4 2012.11   421.8 2009.88   430.4 2013.07
   451.5 2022.08   471.2 2033.17   486.1 2044.04   500.9 2058.18   505.9 2061.43
   525.6 2071.33   540.5 2074.26   604.8 2110.34   619.6 2121.50   634.4 2128.81
   688.8 2160.37   703.7 2166.92   733.4 2183.04   782.8 2216.50   827.3 2240.03
#Mann= 3 , 0 , 0
       0     0.1       0   415.4   0.045       0   430.4     0.1       0
Bank Sta=   415.4,   430.4
Exp/Cntr=0.3,0.1

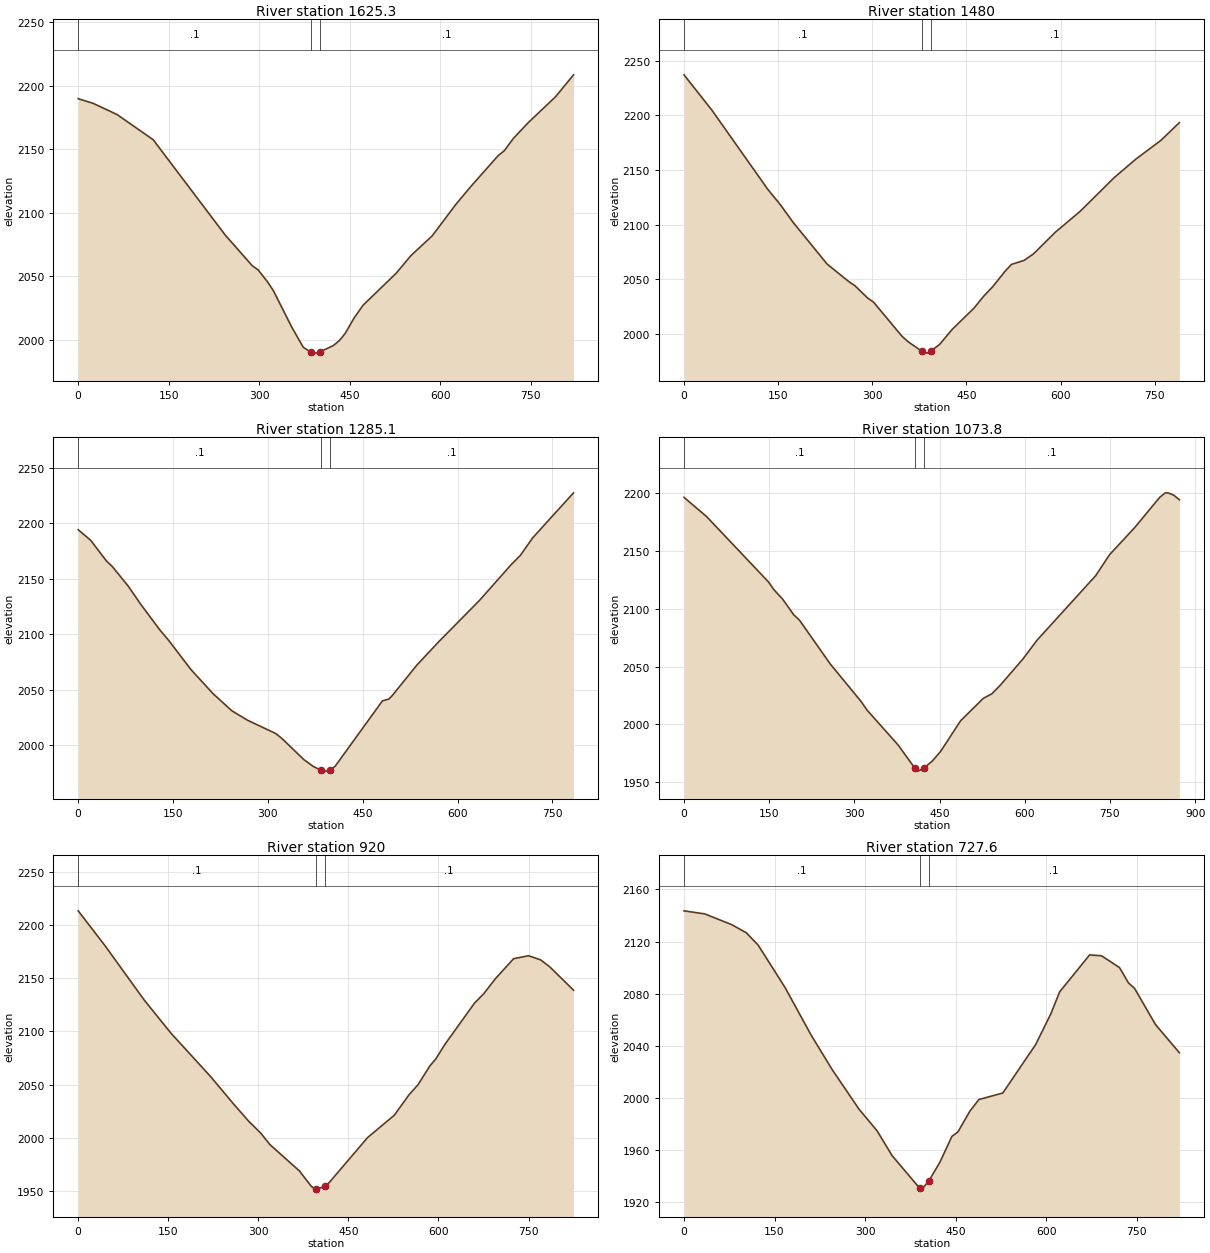
Type RM Length L Ch R = 1 ,1625.3,143.9,145.2,146.6
XS GIS Cut Line= 4
     1857196.450      171219.700     1857415.411      171216.335
     1857791.863      171147.616     1858008.905      171114.903
#Sta/Elev= 30
       0 2189.64    24.9 2185.97    64.7 2177.12   124.4 2157.34   243.8 2082.36
   288.6 2058.25   298.5 2054.90   313.4 2045.86   323.4 2038.81   353.2 2010.73
   373.0 1994.17   385.2 1990.43   392.9 1989.49   400.2 1990.31   422.8 1995.42
   432.7 1999.22   442.6 2004.97   457.5 2017.19   472.4 2027.24   527.1 2052.30
   552.0 2066.41   586.8 2081.69   626.6 2106.80   651.5 2120.88   696.4 2144.93
   706.4 2148.70   721.4 2158.37   746.3 2170.90   791.2 2191.08   821.2 2208.42
#Mann= 3 , 0 , 0
       0     0.1       0   385.2   0.045       0   400.2     0.1       0
Bank Sta=   385.2,   400.2
Exp/Cntr=0.3,0.1

Type RM Length L Ch R = 1 ,1480,191.9,195,198
XS GIS Cut Line= 4
     1857248.391      171395.656     1857543.963      171333.090
     1857776.968      171305.043     1858022.918      171248.949
#Sta/Elev= 30
       0 2237.19    44.6 2204.73   133.7 2132.23   153.5 2118.35   173.4 2102.50
   227.8 2064.14   262.5 2047.98   272.4 2044.17   292.2 2033.12   302.1 2029.09
   347.1 1998.07   357.0 1992.96   378.4 1984.48   387.0 1982.53   393.4 1984.58
   407.0 1990.38   427.0 2004.12   461.9 2023.66   476.9 2034.31   491.9 2043.38
   511.8 2057.68   521.8 2063.73   541.8 2067.41   556.6 2073.28   591.2 2093.01
   630.8 2112.15   685.2 2143.07   719.8 2160.07   759.4 2177.07   789.1 2193.44
#Mann= 3 , 0 , 0
       0     0.1       0   378.4   0.045       0   393.4     0.1       0
Bank Sta=   378.4,   393.4
Exp/Cntr=0.3,0.1

Type RM Length L Ch R = 1 ,1285.1,211.6,211.3,210.9
XS GIS Cut Line= 4
     1857278.595      171518.631     1857546.120      171510.001
     1857809.330      171514.316     1858057.437      171466.852
#Sta/Elev= 30
       0 2194.10    19.8 2184.50    44.6 2166.01    54.5 2160.57    79.3 2143.12
    99.1 2126.78   128.9 2104.00   143.8 2093.92   178.4 2068.06   213.1 2046.50
   242.9 2031.02   267.7 2022.48   312.4 2010.48   322.3 2005.99   357.1 1986.88
   372.0 1980.78   383.7 1977.59   391.8 1976.59   398.7 1977.44   406.7 1981.18
   481.2 2039.88   491.2 2041.48   496.1 2044.20   535.9 2072.25   570.5 2093.28
   634.9 2130.48   684.4 2162.33   699.3 2170.88   719.1 2186.89   783.5 2227.29
#Mann= 3 , 0 , 0
       0     0.1       0   383.7   0.045       0   398.7     0.1       0
Bank Sta=   383.7,   398.7
Exp/Cntr=0.3,0.1

Type RM Length L Ch R = 1 ,1073.8,154,153.8,153.6
XS GIS Cut Line= 4
     1857236.886      171635.717     1857538.194      171717.594
     1857842.777      171717.594     1858094.204      171672.933
#Sta/Elev= 30
       0 2196.58    39.6 2180.01   148.7 2123.37   158.6 2116.46   173.5 2108.58
   193.3 2094.83   203.2 2090.35   257.7 2052.20   312.2 2019.63   322.2 2012.46
   377.2 1982.04   406.8 1961.91   412.1 1959.55   421.8 1961.98   437.1 1968.23
   452.0 1976.73   487.0 2003.14   526.9 2022.51   541.9 2026.47   556.9 2033.94
   596.8 2056.66   621.7 2072.96   724.9 2128.79   749.4 2146.99   793.6 2170.42
   837.8 2196.70   847.6 2200.49   852.5 2200.43   862.4 2198.43   872.2 2194.52
#Mann= 3 , 0 , 0
       0     0.1       0   406.8   0.045       0   421.8     0.1       0
Bank Sta=   406.8,   421.8
Exp/Cntr=0.3,0.1

Type RM Length L Ch R = 1 ,920,192.6,192.5,192.2
XS GIS Cut Line= 4
     1857266.362      171842.048     1857534.919      171868.248
     1857885.354      171864.973     1858088.409      171838.773
#Sta/Elev= 30
       0 2213.69    45.0 2180.60   109.9 2129.67   154.9 2098.14   219.9 2057.91
   259.8 2031.00   284.6 2015.05   304.4 2004.00   319.2 1993.46   368.6 1968.49
   388.3 1953.98   395.5 1951.49   398.2 1951.41   410.5 1954.18   417.9 1957.49
   482.1 2000.06   526.5 2021.07   551.2 2040.46   566.0 2049.80   585.7 2067.52
   595.6 2074.10   610.4 2087.53   660.2 2126.83   675.2 2135.40   695.2 2149.93
   725.2 2168.57   750.1 2171.37   770.1 2167.50   785.1 2161.05   825.0 2138.90
#Mann= 3 , 0 , 0
       0     0.1       0   395.5   0.045       0   410.5     0.1       0
Bank Sta=   395.5,   410.5
Exp/Cntr=0.3,0.1

Type RM Length L Ch R = 1 ,727.6,166.4,165.7,165
XS GIS Cut Line= 4
     1857254.258      172026.880     1857508.718      172048.379
     1857846.052      172048.379     1858071.249      172084.213
#Sta/Elev= 30
       0 2143.57    34.4 2141.21    78.6 2133.06   103.1 2126.78   122.8 2117.29
   167.0 2085.08   211.2 2047.76   245.5 2021.74   290.1 1991.31   319.9 1974.78
   344.7 1955.80   390.7 1930.59   394.3 1930.03   405.7 1936.42   424.0 1950.68
   443.9 1970.54   453.8 1973.86   473.6 1989.85   488.5 1998.76   528.2 2003.79
   582.8 2041.10   607.6 2064.38   622.4 2081.42   672.0 2109.73   691.8 2109.07
   721.6 2100.00   736.5 2088.17   746.4 2084.13   781.1 2056.35   820.7 2034.72
#Mann= 3 , 0 , 0
       0     0.1       0   390.7   0.045       0   405.7     0.1       0
Bank Sta=   390.7,   405.7
Exp/Cntr=0.3,0.1

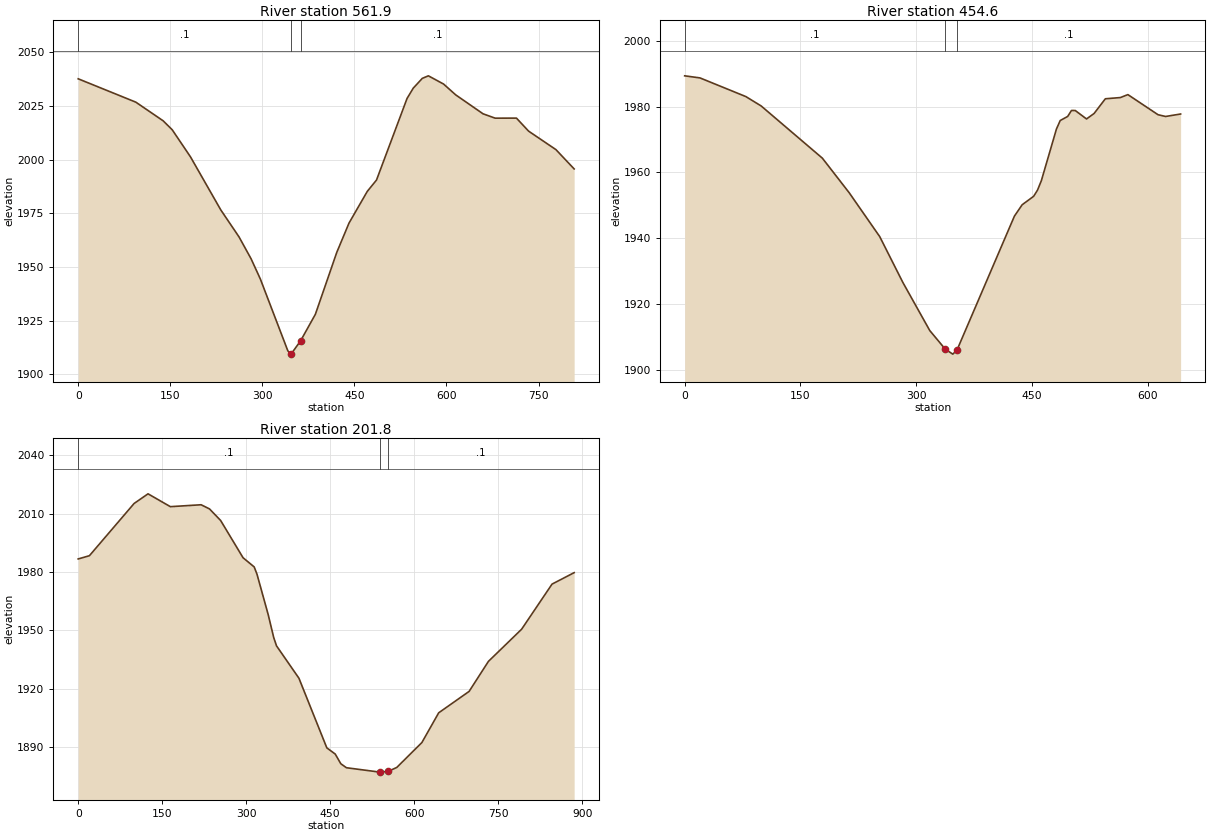
Type RM Length L Ch R = 1 ,561.9,106.5,107.3,108.1
XS GIS Cut Line= 4
     1857269.637      172218.683     1857551.294      172212.133
     1857810.027      172199.033     1858072.034      172146.631
#Sta/Elev= 30
       0 2037.69    93.9 2026.80   138.4 2018.11   153.2 2013.92   182.9 2001.32
   232.3 1976.58   262.0 1964.01   281.7 1953.78   296.7 1944.41   341.5 1910.93
   346.5 1909.37   347.4 1909.61   362.4 1915.61   386.4 1927.94   421.2 1956.75
   441.2 1970.45   471.0 1985.23   486.0 1990.51   535.8 2028.55   545.8 2033.31
   560.6 2037.90   570.5 2039.08   595.2 2035.26   615.0 2030.21   659.6 2021.37
   679.3 2019.35   714.0 2019.37   733.8 2013.30   778.3 2004.69   808.0 1995.69
#Mann= 3 , 0 , 0
       0     0.1       0   347.4   0.045       0   362.4     0.1       0
Bank Sta=   347.4,   362.4
Exp/Cntr=0.3,0.1

Type RM Length L Ch R = 1 ,454.6,272,252.7,233.4
XS GIS Cut Line= 4
     1857300.707      172345.272     1857556.226      172312.054
     1857760.642      172309.499     1857934.395      172260.950
#Sta/Elev= 30
       0 1989.31    19.8 1988.68    79.3 1983.01    99.1 1980.17   178.4 1964.33
   213.1 1953.86   252.7 1940.54   282.6 1926.67   317.5 1912.06   337.8 1906.35
   347.4 1904.90   352.8 1906.14   427.2 1946.76   437.2 1950.20   452.1 1952.77
   457.1 1954.64   462.1 1957.52   481.6 1973.15   486.5 1975.75   496.2 1976.99
   501.1 1978.80   506.0 1978.79   520.6 1976.23   530.4 1977.89   545.0 1982.35
   564.5 1982.72   574.2 1983.61   613.2 1977.52   623.0 1976.98   642.5 1977.73
#Mann= 3 , 0 , 0
       0     0.1       0   337.8   0.045       0   352.8     0.1       0
Bank Sta=   337.8,   352.8
Exp/Cntr=0.3,0.1

Type RM Length L Ch R = 1 ,201.8,196.1,201.8,235.5
XS GIS Cut Line= 4
     1857269.637      172477.415     1857749.844      172537.575
     1857852.603      172415.189     1858006.532      172228.508
#Sta/Elev= 30
       0 1986.66    20.0 1988.32    99.8 2015.16   124.7 2020.13   164.6 2013.53
   219.5 2014.51   234.5 2012.37   254.4 2006.41   294.4 1987.28   314.3 1982.55
   319.3 1978.80   339.3 1958.04   349.2 1946.21   354.2 1941.97   394.2 1925.34
   444.0 1889.55   459.0 1886.37   469.0 1881.39   479.0 1879.34   538.2 1877.10
   538.9 1877.08   553.2 1877.43   568.9 1879.48   613.8 1892.30   643.8 1907.57
   698.1 1918.57   732.6 1934.00   791.9 1950.54   846.2 1973.72   885.7 1979.61
#Mann= 3 , 0 , 0
       0     0.1       0   538.2   0.045       0   553.2     0.1       0
Bank Sta=   538.2,   553.2
Exp/Cntr=0.3,0.1